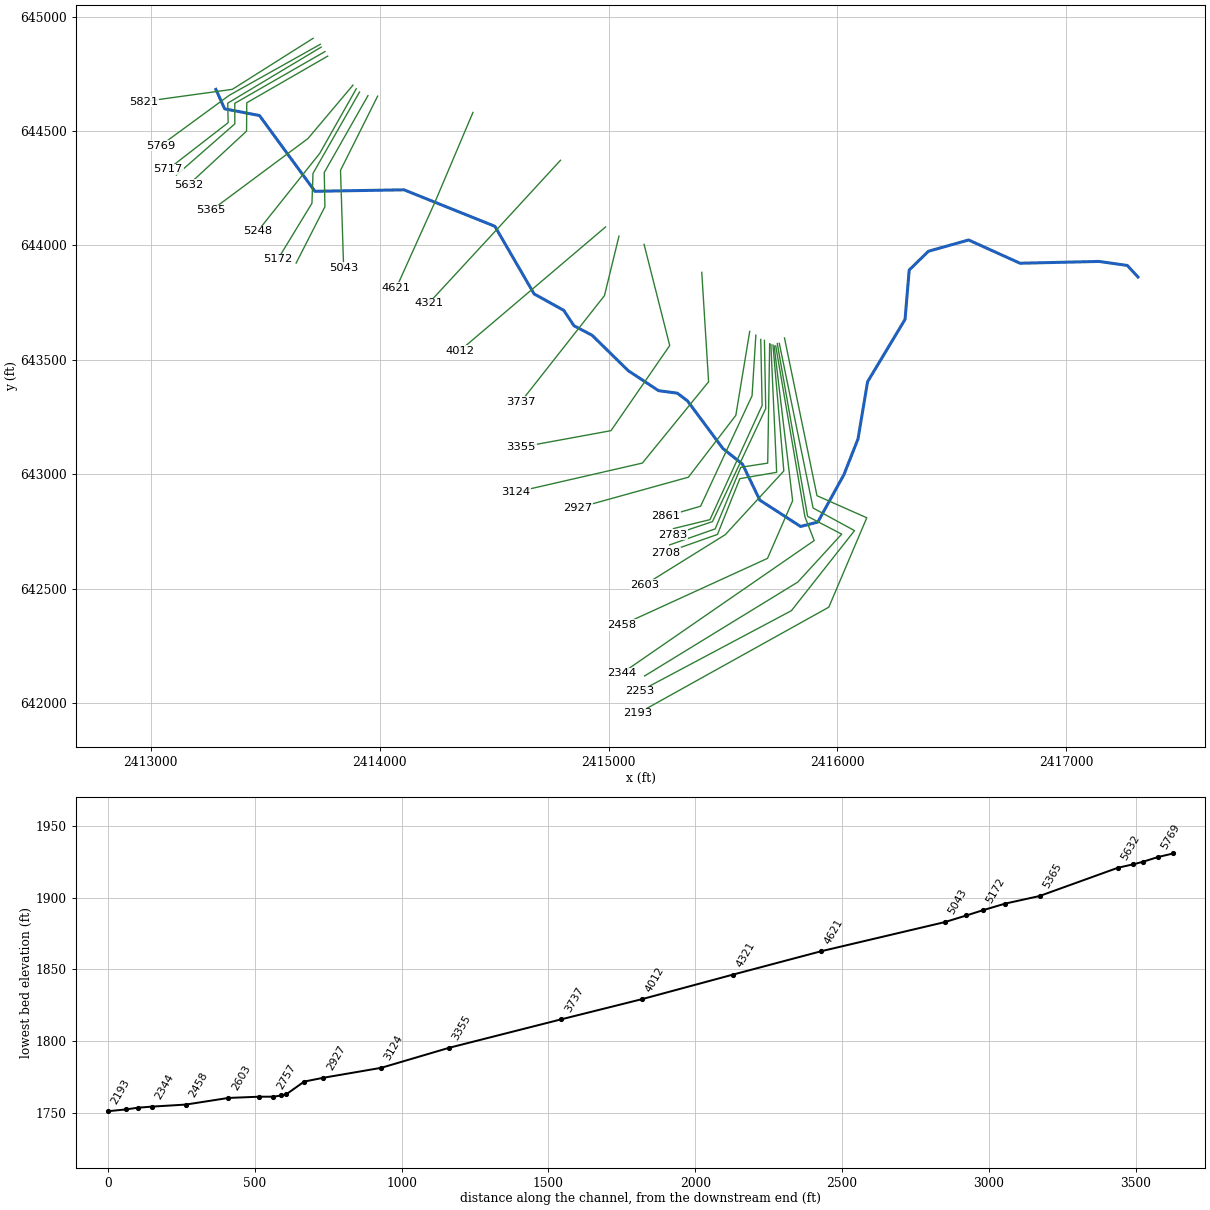
--- NFSBPOTMC_T2.prj (project) ---

Proj Title=NFSBPOTMC_T2
Current Plan=p01
Default Exp/Contr=0,0
English Units
Geom File=g01
Flow File=f01
Plan File=p01
BEGIN DESCRIPTION:
Stream Name: North Fork South Branch Potomac River Tributary 2
Flood Zone: Approximate
Pendleton County, West Virginia
HEC-RAS Version: 5.0.7
Hydrology Method:
Regression equation
END DESCRIPTION:
DSS Export Rating Curves= 0
DSS Export Rating Curve Sorted= 0
DSS Export Volume Flow Curves= 0
DXF OffsetX= 0
DXF OffsetY= 0
DXF ScaleX= 0
DXF ScaleY= 0

--- NFSBPOTMC_T2.p01 (plan) ---

Plan Title=Floodplain
Program Version=5.07
Geom File=g01
Flow File=f01
Subcritical Flow
K Sum by GR= 0
Std Step Tol= 0.01
Critical Tol= 0.01
Num of Std Step Trials= 20
Max Error Tol= 0.3
Flow Tol Ratio= 0.001
Split Flow NTrial= 30
Split Flow Tol= 0.02
Split Flow Ratio= 0.02
Log Output Level= 0
Friction Slope Method= 1
Unsteady Friction Slope Method= 2
Unsteady Bridges Friction Slope Method= 1
Parabolic Critical Depth
Global Vel Dist= 0 , 0 , 0
Global Log Level= 0
CheckData=False
Encroach Param=-1 ,0,0, 0
Mapping Interval=1HOUR
Computation Time Step Use Courant=        0
Computation Time Step Use Time Series=    0
Computation Time Step Count To Double=0
Computation Time Step Max Doubling=0
Computation Time Step Max Halving=0
Computation Time Step Residence Courant=0
Run HTab= 0
Run UNet= 0
Run Sediment= 0
Run PostProcess= 0
Run WQNet= 0
Run RASMapper= 0
UNET Theta= 0
UNET Theta Warmup= 0
UNET ZTol= 0
UNET ZSATol= 0
UNET MxIter= 0
UNET Max Iter WO Improvement= 0
UNET MaxInSteps= 0
UNET DtIC= 0
UNET DtMin= 0
UNET MaxCRTS= 0
UNET WFStab= 0
UNET SFStab= 0
UNET WFX= 1
UNET SFX= 1
UNET 1D Methodology=Finite Difference
UNET DSS MLevel= 1
UNET Pardiso=0
UNET DZMax Abort= 0
UNET Use Existing IB Tables= 0
UNET Froude Reduction=False
UNET Froude Limit= 0
UNET Froude Power= 0
UNET D1 Cores= 0
UNET D2 Coriolis=0
UNET D2 Cores= 0
UNET D2 Theta= 1
UNET D2 Theta Warmup= 1
UNET D2 Z Tol= 0.01
UNET D2 Volume Tol= 0.01
UNET D2 Max Iterations= 20
UNET D2 Equation= 0
UNET D2 RampUpFraction=0.1
UNET D2 TimeSlices= 1
UNET D2 BCVolumeCheck=0
UNET D1D2 MaxIter= 0
UNET D1D2 ZTol=0.01
UNET D1D2 QTol=0.1
UNET D1D2 MinQTol=1
Write IC File= 0
Write IC File at Fixed DateTime=0
Write IC File at Sim End=0
Echo Input=False
Echo Parameters=False
Echo Output=False
Write Detailed= 0
HDF Write Warmup=0
HDF Write Time Slices=0
HDF Flush=0
HDF Face Node Velocities=0
HDF Compression= 1
HDF Chunk Size= 1
HDF Spatial Parts= 1
HDF Use Max Rows=0
HDF Fixed Rows= 1
Calibration Method= 0
Calibration Iterations= 20
Calibration Max Change=0.05
Calibration Tolerance=0.2
Calibration Maximum=1.5
Calibration Minimum=0.5
Calibration Optimization Method= 1
WQ AD Non Conservative
WQ ULTIMATE=-1
WQ Max Comp Step=1HOUR
WQ Output Interval=15MIN
WQ Output Selected Increments= 0
WQ Output face flow=0
WQ Output face velocity=0
WQ Output face area=0
WQ Output face dispersion=0
WQ Output cell volume=0
WQ Output cell surface area=0
WQ Output cell continuity=0
WQ Output cumulative cell continuity=0
WQ Output face conc=0
WQ Output face dconc_dx=0
WQ Output face courant=0
WQ Output face peclet=0
WQ Output face adv mass=0
WQ Output face disp mass=0
WQ Output cell mass=0
WQ Output cell source sink temp=0
WQ Output nsm pathways=0
WQ Output nsm derived pathways=0
WQ Output MaxMinRange=-1
WQ Daily Max Min Mean=-1
WQ Daily Range=0
WQ Daily Time=0
WQ Create Restart=0
WQ Fixed Restart=0
WQ System Summary=0
WQ Write To DSS=0
WQ Use Fixed Temperature=0
Sorting and Armoring Iterations= 10
XS Update Threshold= 0.02
Bed Roughness Predictor= 0
Hydraulics Update Threshold= 0.02
Energy Slope Method= 1
Volume Change Method= 1
Sediment Retention Method= 0
XS Weighting Method= 0
Number of US Weighted Cross Sections= 1
Number of DS Weighted Cross Sections= 1
Upstream XS Weight=0
Main XS Weight=1
Downstream XS Weight=0
Number of DS XS's Weighted with US Boundary= 1
Upstream Boundary Weight= 1
Weight of XSs Associated with US Boundary= 0
Number of US XS's Weighted with DS Boundary= 1
Downstream Boundary Weight= 0.5
Weight of XSs Associated with DS Boundary= 0.5
Percentile Method= 0
Sediment Output Level= 3
Mass or Volume Output= 0
Output Increment Type= 1
Profile and TS Output Increment= 1
XS Output Flag= 0
XS Output Increment= 10
Write Gradation File= 0
Read Gradation Hotstart= 0
Write HDF5 File= 1
Write Binary Output= 1
Write DSS Sediment File= 0
SV Curve= 0
Specific Gage Flag= 0

--- NFSBPOTMC_T2.f01 (steady flow) ---

Flow Title=Flows
Program Version=5.07
Number of Profiles= 6
Profile Names=P100yr,P10yr,P25yr,P50yr,P500yr,P101yr
River Rch & RM=NFSBPOTMC_T2,Main            ,5821
     588     275     388     485     861     715
River Rch & RM=NFSBPOTMC_T2,Main            ,5043
     654     305     432     539     959     795
Boundary for River Rch & Prof#=NFSBPOTMC_T2,Main            , 1
Up Type= 0
Dn Type= 3
Dn Slope=0.0202
Boundary for River Rch & Prof#=NFSBPOTMC_T2,Main            , 2
Up Type= 0
Dn Type= 3
Dn Slope=0.0202
Boundary for River Rch & Prof#=NFSBPOTMC_T2,Main            , 3
Up Type= 0
Dn Type= 3
Dn Slope=0.0202
Boundary for River Rch & Prof#=NFSBPOTMC_T2,Main            , 4
Up Type= 0
Dn Type= 3
Dn Slope=0.0202
Boundary for River Rch & Prof#=NFSBPOTMC_T2,Main            , 5
Up Type= 0
Dn Type= 3
Dn Slope=0.0202
Boundary for River Rch & Prof#=NFSBPOTMC_T2,Main            , 6
Up Type= 0
Dn Type= 3
Dn Slope=0.0202
DSS Import GetInterval= 0
DSS Import GetPeak= 0
DSS Import FillOption= 0

--- NFSBPOTMC_T2.g01 (geometry) ---

Geom Title=Geometry
Program Version=5.07

River Reach=NFSBPOTMC_T2    ,Main
Reach XY= 30
2413284.10600001644682.1250000152413322.59900004      644597.059
2413474.56799999644567.967000008     2413716.903      644236.831
2414106.26800001644243.2830000072414503.38300002644083.881999999
2414674.69000003643788.4660000212414804.34400001643716.578999996
2414848.83700001643649.3380000142414927.92300004643607.936000019
2415086.04900002643452.9360000042415218.37900001643365.704000011
2415300.54400003643354.6170000142415344.84400004643321.143000007
2415499.49599999643113.1270000192415585.20400003643044.665000021
2415661.01000002642887.3220000122415839.02700004642772.278000012
     2415914.491 642791.593000012416028.49700004642998.806000009
2416089.98300001643154.6060000212416131.96900001643404.800999999
     2416295.542 643677.179000022416313.77599999643892.762999997
2416397.75500003643974.8820000142416573.35400003 644024.13000001
2416797.91100001643922.476999998     2417142.924      643930.338
2417266.88600001      643912.7942417313.31893227643862.299548313

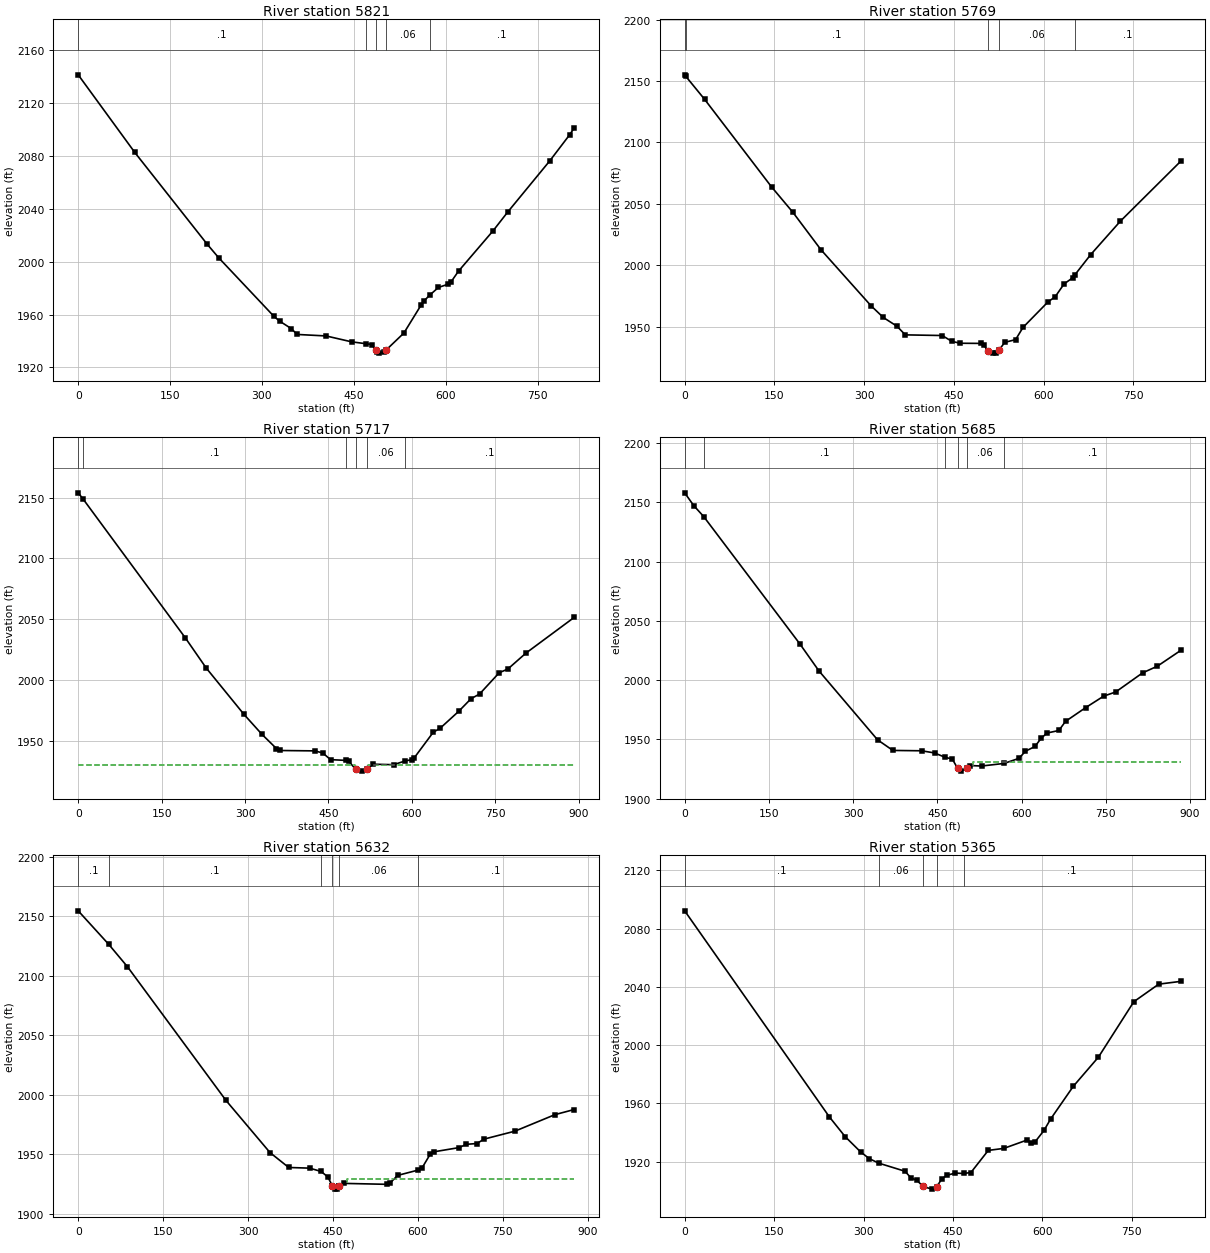
Type RM Length L Ch R = 1 ,5821    ,52.3,52.3,52.3
XS GIS Cut Line= 3
2413708.88005633644905.2139485062413356.13181149644682.337385255
2412967.35464852644628.712948984
#Sta/Elev= 30
       0 2141.23    92.4 2082.54   210.7 2013.11   229.6 2002.81   319.5 1958.67
     329 1954.98   347.9 1949.39   357.4 1944.97   404.7 1943.84   446.4 1939.38
  470.271937.942   479.2 1937.37   485.4  1933.4   487.3 1931.93   491.3 1930.85
   499.2 1931.73   503.2 1933.43   531.7 1946.02     560 1967.31   564.7 1970.35
  574.16 1974.83   588.2 1980.53   604.4 1983.02   608.4  1984.5   620.9 1992.83
   677.1  2023.2   701.3 2037.55     770 2076.26   802.3 2095.88   809.7 2101.03
#Mann= 5 ,-1 , 0
       0      .1       0  470.27     .06       0   485.4    .045       0
   503.2     .06       0  574.16      .1       0
Bank Sta=485.4,503.2
XS Rating Curve= 0 ,0
Exp/Cntr(USF)=0,0
Exp/Cntr=0.3,0.1

Type RM Length L Ch R = 1 ,5769    ,39.9,52.5,67.8
XS GIS Cut Line= 3
2413740.45276363 644879.118645452413342.72570242644656.363048936
2413041.55660883644435.875736765
#Sta/Elev= 30
       0 2155.08    1.642153.983    33.2 2135.19   145.4 2063.67   180.8 2043.13
   227.7 2012.65   311.5 1966.94   332.1 1957.37     355 1950.23   368.8 1943.22
   430.5 1942.68   446.7  1937.9   460.8 1936.39   495.5 1936.26   500.5 1934.73
   506.5 1930.35   515.3 1928.34   520.3 1928.66   525.2  1930.7   535.2 1937.15
   553.2 1939.32   565.7 1949.35   607.3 1970.02   619.4 1974.27   634.3 1984.73
   649.2 1989.91  651.861991.835   678.9 2008.69   728.5  2035.9   829.1 2084.58
#Mann= 5 ,-1 , 0
       0      .1       0    1.64      .1       0   506.5    .045       0
   525.2     .06       0  651.86      .1       0
Bank Sta=506.5,525.2
XS Rating Curve= 0 ,0
Exp/Cntr=0.5,0.3

Type RM Length L Ch R = 1 ,5717    ,32.3,31.9,30.5
XS GIS Cut Line= 4
2413744.07109263644866.6713849362413336.02264788 644622.00989445
2413337.69841152644536.545949143 2413076.2792847644333.778549494
#Sta/Elev= 30
       0 2153.91    8.962148.699   192.8 2034.51   230.1 2009.87   298.2 1971.63
   330.6 1955.18   356.5 1943.57   362.4 1941.93     426 1941.61     440 1939.86
   453.9 1934.41  482.061933.782   486.9 1932.94   498.9 1926.58   510.9 1924.96
   518.9  1926.6   530.9 1930.65   567.4 1930.25  588.121933.355   600.4 1934.41
   604.5 1935.93   638.7 1956.97   651.1 1960.27   684.3 1974.09   706.7 1984.59
   721.9 1988.36   757.4 2005.95   772.7 2008.91   805.4 2022.06   892.1  2051.4
#Mann= 6 ,-1 , 0
       0      .1       0    8.96      .1       0  482.06     .06       0
   498.9    .045       0   518.9     .06       0  588.12      .1       0
#XS Ineff= 2 , 0
          498.64 1930.34  520.49         1930.23
Permanent Ineff=
       F       F
Bank Sta=498.9,518.9
XS Rating Curve= 0 ,0
Exp/Cntr(USF)=0,0
Exp/Cntr=0.5,0.3

Type RM Length L Ch R = 1 ,5685    ,52.6,52.1,52
XS GIS Cut Line= 4
     2413760.718      644847.2532413366.72189093644621.240972653
 2413367.0242751644531.5186582432413111.70900016644307.841645291
#Sta/Elev= 30
       0 2157.96    16.1 2147.22   33.982137.881   205.2 2030.53   239.1 2007.81
   343.5 1949.68   370.9  1940.7   421.9 1940.41     445  1938.6  464.48 1934.79
   476.6 1933.51   486.31925.498   492.6 1923.25   502.21925.646   508.7 1927.96
   528.8 1927.55   568.8 1929.73   595.6 1934.04   606.9 1940.04     624 1944.03
   634.7 1950.84   645.4 1955.38   666.5 1957.52   678.4 1965.21   714.5 1976.88
   746.4 1986.51   767.7 1989.99   815.5 2006.07   842.1 2011.79   883.4 2024.99
#Mann= 6 ,-1 , 0
       0      .1       0   33.98      .1       0  464.48     .06       0
   486.3    .045       0   502.2     .06       0   568.8      .1       0
#XS Ineff= 2 , 0
                          513.24         1931.23
Permanent Ineff=
       F       F
Bank Sta=486.3,502.2
XS Rating Curve= 0 ,0
Exp/Cntr=0.5,0.3

Type RM Length L Ch R = 1 ,5632    ,275.7,267.2,254.3
XS GIS Cut Line= 4
2413772.90070846644827.5017394162413419.12838583644623.617164011
2413418.19740604644499.7968510932413165.90188122644266.120922204
#Sta/Elev= 30
       0 2154.42   53.622126.438      87 2107.49     261 1995.31   338.8 1951.53
   371.8 1939.04   408.7 1938.48  429.071935.698   440.9 1931.09     449 1923.55
     449 1923.48     453 1920.87   457.1 1921.26     461 1923.68     461 1923.69
     469 1925.69   545.2  1924.9   551.1  1926.1   564.1 1932.37  600.131936.821
   607.7 1938.97   621.8  1950.2   627.7 1952.14   673.2 1955.76   685.2 1958.46
   704.2 1959.13   716.8 1962.83   771.3  1969.5   842.2  1983.4     876 1987.67
#Mann= 6 ,-1 , 0
       0      .1       0   53.62      .1       0  429.07     .06       0
     449    .045       0     461     .06       0  600.13      .1       0
#XS Ineff= 2 , 0
                          474.41         1929.22
Permanent Ineff=
       F       F
Bank Sta=449,461
XS Rating Curve= 0 ,0
Exp/Cntr(USF)=0,0
Exp/Cntr=0.3,0.1

Type RM Length L Ch R = 1 ,5365    ,114.2,117.2,120.8
XS GIS Cut Line= 3
     2413883.222      644700.6642413686.49680032644467.270177673
      2413263.76      644152.953
#Sta/Elev= 30
       0 2092.24   242.9 1950.65   269.1 1937.24   295.3 1926.64   309.9 1922.03
  325.261919.028   369.7  1913.4   379.6 1908.83   389.7 1907.16   399.7 1903.03
   399.7 1903.02   414.6 1901.14   422.6 1902.58   431.1 1908.05   439.5  1910.6
     454 1912.17  467.821911.879   480.2 1912.55   509.3 1927.73   535.4 1929.11
     574  1934.8   580.7 1933.11   587.4 1933.38   602.7  1941.4   614.1 1949.38
     652 1971.77   694.1 1991.77   753.5 2029.84   795.3 2041.89     832 2043.79
#Mann= 5 ,-1 , 0
       0      .1       0  325.26     .06       0   399.7    .045       0
   422.6     .06       0  467.82      .1       0
Bank Sta=399.7,422.6
XS Rating Curve= 0 ,0
Exp/Cntr=0.3,0.1

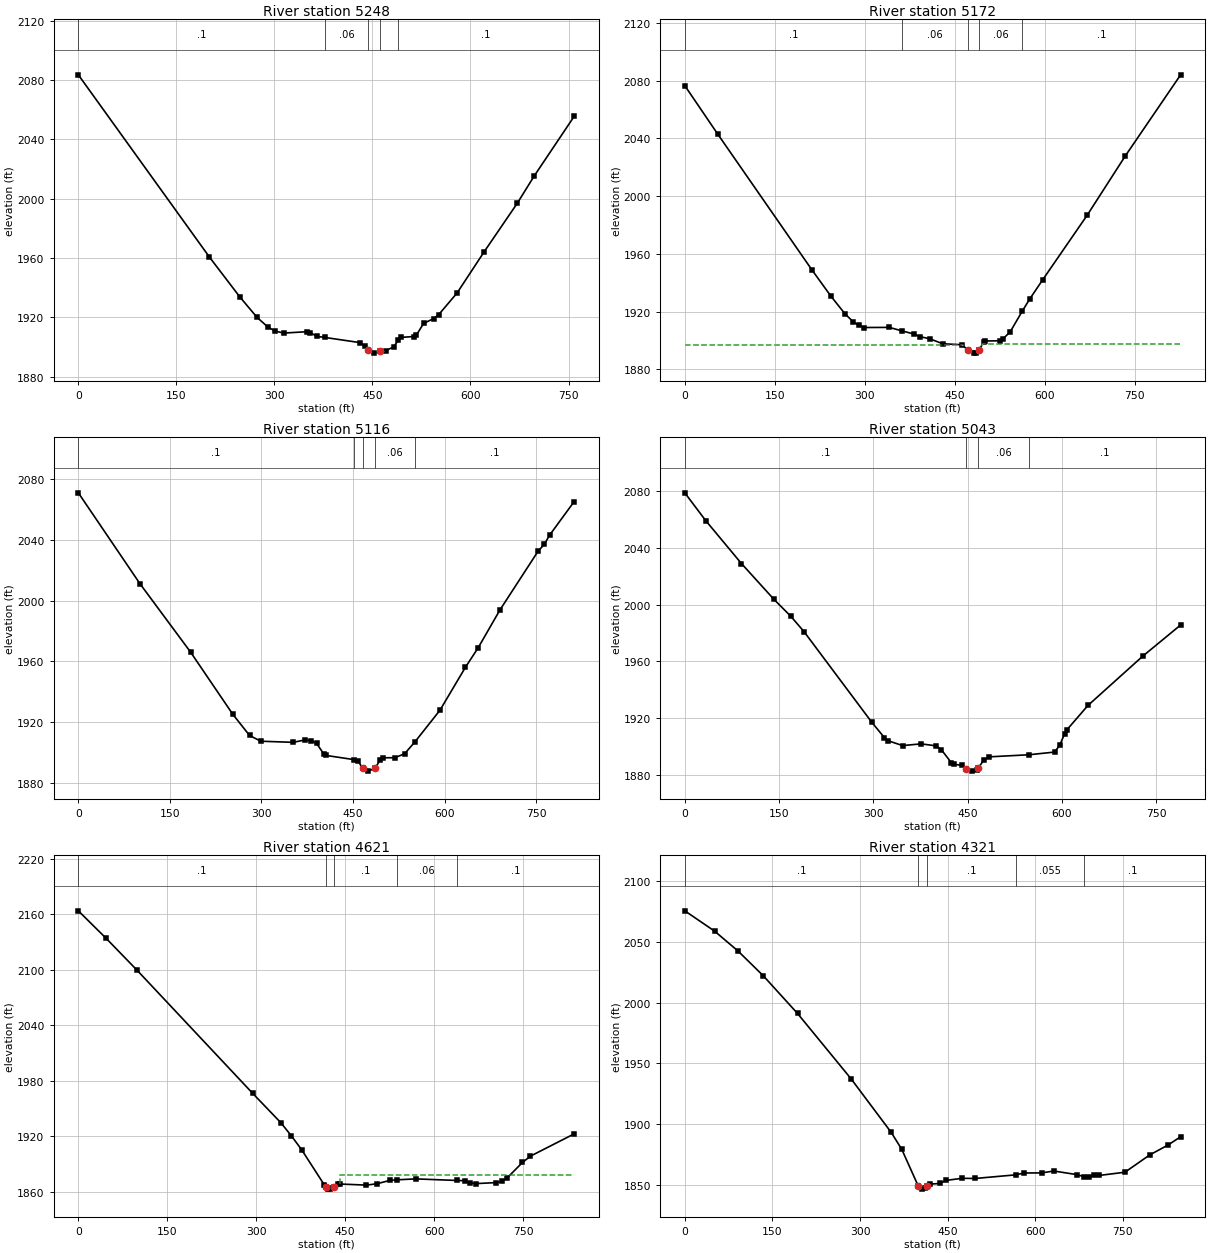
Type RM Length L Ch R = 1 ,5248    ,66.7,75.9,84.8
XS GIS Cut Line= 3
2413897.52732559644684.7210249552413737.89387434 644402.48908313
  2413467.155541644062.789098853
#Sta/Elev= 30
       0 2083.59   200.6 1960.63     247 1933.81   273.4 1919.98     290 1913.46
   300.8 1910.76   314.5 1909.38   349.3 1910.29     355 1909.69   364.7 1907.17
  377.271906.423   431.2 1902.93   438.4 1900.62   443.61897.913   451.6 1895.85
   461.8 1897.13   470.5 1897.62   482.3 1899.98  489.581904.592   494.1 1906.49
   514.1 1907.06   516.9 1907.79   528.3 1915.91   543.7 1919.16   551.1 1921.68
   579.5 1936.45   620.4 1963.89   671.6 1996.97   697.1  2015.1   758.6 2055.57
#Mann= 5 ,-1 , 0
       0      .1       0  377.27     .06       0   443.6    .045       0
   461.8     .06       0  489.58      .1       0
Bank Sta=443.6,461.8
XS Rating Curve= 0 ,0
Exp/Cntr(USF)=0,0
Exp/Cntr=0.5,0.3

Type RM Length L Ch R = 1 ,5172    ,56.6,56,56.6
XS GIS Cut Line= 4
     2413911.844      644670.5682413708.51870519644314.943998428
2413703.92611205644184.542155337   2413555.13175643940.288658805
#Sta/Elev= 30
       0 2076.51    54.9 2042.92   211.7 1948.95   243.8 1930.48   267.3 1918.24
   280.7 1912.91   289.9 1910.48   299.1 1908.97   340.6 1909.06   361.51906.676
   381.7 1904.46   391.3 1902.68   408.1 1901.19   429.7 1897.71   461.7 1897.05
   471.91893.266   481.7 1891.23   485.7 1891.28   490.8 1893.43   497.8 1899.04
   500.3 1899.63   525.8 1899.79   529.8 1901.01   542.1 1905.92  562.361920.405
   574.8 1928.79   596.2 1941.98   670.3 1986.69   734.1 2027.92   826.1    2084
#Mann= 5 ,-1 , 0
       0      .1       0   361.5     .06       0   471.9    .045       0
   490.8     .06       0  562.36      .1       0
#XS Ineff= 2 , 0
          464.32    1897  494.54          1897.7
Permanent Ineff=
       F       F
Bank Sta=471.9,490.8
XS Rating Curve= 0 ,0
Exp/Cntr=0.5,0.3

Type RM Length L Ch R = 1 ,5116    ,73.2,73.5,73.5
XS GIS Cut Line= 4
     2413948.723      644654.7992413757.70225049644318.929482792
2413760.68981596 644169.578714562413634.83138679643923.221507076
#Sta/Elev= 30
       0 2071.19   101.1 2011.15     184 1966.06     253 1925.14   280.6  1911.1
     299 1907.32   351.9 1906.59     371 1908.12   381.8 1907.69   390.4 1905.85
   402.4 1898.77   406.4 1897.91  451.421895.199   458.4 1894.35   465.9 1889.34
   474.4 1887.59   486.4  1889.4   494.5 1895.15   498.5  1896.4   518.5 1896.43
   534.5 1899.03     5511906.623   592.6 1927.82   634.3 1956.13   655.2 1969.02
   690.8 1993.93   753.3 2032.68   763.4 2037.17   772.4  2043.4   812.4 2065.41
#Mann= 5 ,-1 , 0
       0      .1       0  451.42     .06       0   465.9    .045       0
   486.4     .06       0     551      .1       0
Bank Sta=465.9,486.4
XS Rating Curve= 0 ,0
Exp/Cntr=0.5,0.3

Type RM Length L Ch R = 1 ,5043    ,426.6,421.4,415.5
XS GIS Cut Line= 3
     2413991.077      644652.6822413828.78644182644328.433462264
2413842.42038836643902.457583333
#Sta/Elev= 30
       0 2078.49    33.3 2058.96    90.1 2028.82   141.7  2003.7   168.5 1991.84
   189.9 1980.83   297.2 1917.45   317.6 1906.48   323.5 1904.32   346.4 1900.92
   376.1 1902.12   400.2 1900.71   408.2 1897.98   424.2 1888.81   428.2 1887.74
   440.2 1887.13   447.4 1884.72   456.2 1882.97   464.2 1883.83   466.8 1885.12
   476.2  1891.1   484.2    1893  547.691894.477   588.3 1896.36   596.3 1901.07
   604.3 1909.22   608.3 1912.21   641.3 1929.09   728.3 1963.64   788.8 1985.63
#Mann= 4 ,-1 , 0
       0      .1       0   447.4    .045       0   466.8     .06       0
  547.69      .1       0
Bank Sta=447.4,466.8
XS Rating Curve= 0 ,0
Exp/Cntr=0.3,0.1

Type RM Length L Ch R = 1 ,4621    ,303.8,300,295.2
XS GIS Cut Line= 3
2414407.47650352644581.419918739     2414241.663       644190.07
     2414072.786      643815.353
#Sta/Elev= 30
       0 2163.82    46.2 2134.49    98.3 2100.01   293.8  1966.4   341.2  1934.7
     359 1920.48   376.4  1905.4   414.4 1867.55   417.41865.132   420.5 1863.27
   424.1 1862.64   428.5 1863.54   431.11865.076   437.3 1867.71   441.7 1868.15
   485.6 1866.98   503.1  1868.4     525 1872.03  537.651872.716   568.9 1873.73
  638.831872.004   652.3 1871.74   661.1 1869.43   669.8  1868.6   704.9 1869.72
   713.7 1870.91   722.5 1874.42   748.8 1891.47   762.3 1898.35     836 1922.42
#Mann= 5 ,-1 , 0
       0      .1       0   417.4    .045       0   431.1      .1       0
  537.65     .06       0  638.83      .1       0
#XS Ineff= 2 , 0
       0                  441.63       0 1878.12
Permanent Ineff=
       F       F
Bank Sta=417.4,431.1
XS Rating Curve= 0 ,0
Exp/Cntr=0.3,0.1

Type RM Length L Ch R = 1 ,4321    ,309.9,309.7,308.9
XS GIS Cut Line= 3
2414789.94073321644372.377881633     2414514.863      644073.212
     2414214.665      643748.197
#Sta/Elev= 30
       0 2075.65    50.9 2058.95    91.1 2042.54   134.7 2021.98     193 1991.08
   284.6 1937.29   353.4 1893.07   371.5 1879.08   399.6 1848.97   406.6 1846.37
     411 1846.93     415 1848.78   419.5  1850.5   436.1 1851.02   447.8  1853.6
   474.9 1855.29   496.7 1855.14  566.131858.115   580.8 1859.65     611 1859.75
   631.8 1861.29   671.4 1858.31  683.631856.582   691.2 1855.96   699.7 1857.79
   709.1 1857.62   753.5 1860.31   795.9 1874.55   827.1 1882.66   848.8 1889.52
#Mann= 5 ,-1 , 0
       0      .1       0   399.6    .045       0     415      .1       0
  566.13    .055       0  683.63      .1       0
Bank Sta=399.6,415
XS Rating Curve= 0 ,0
Exp/Cntr=0.3,0.1

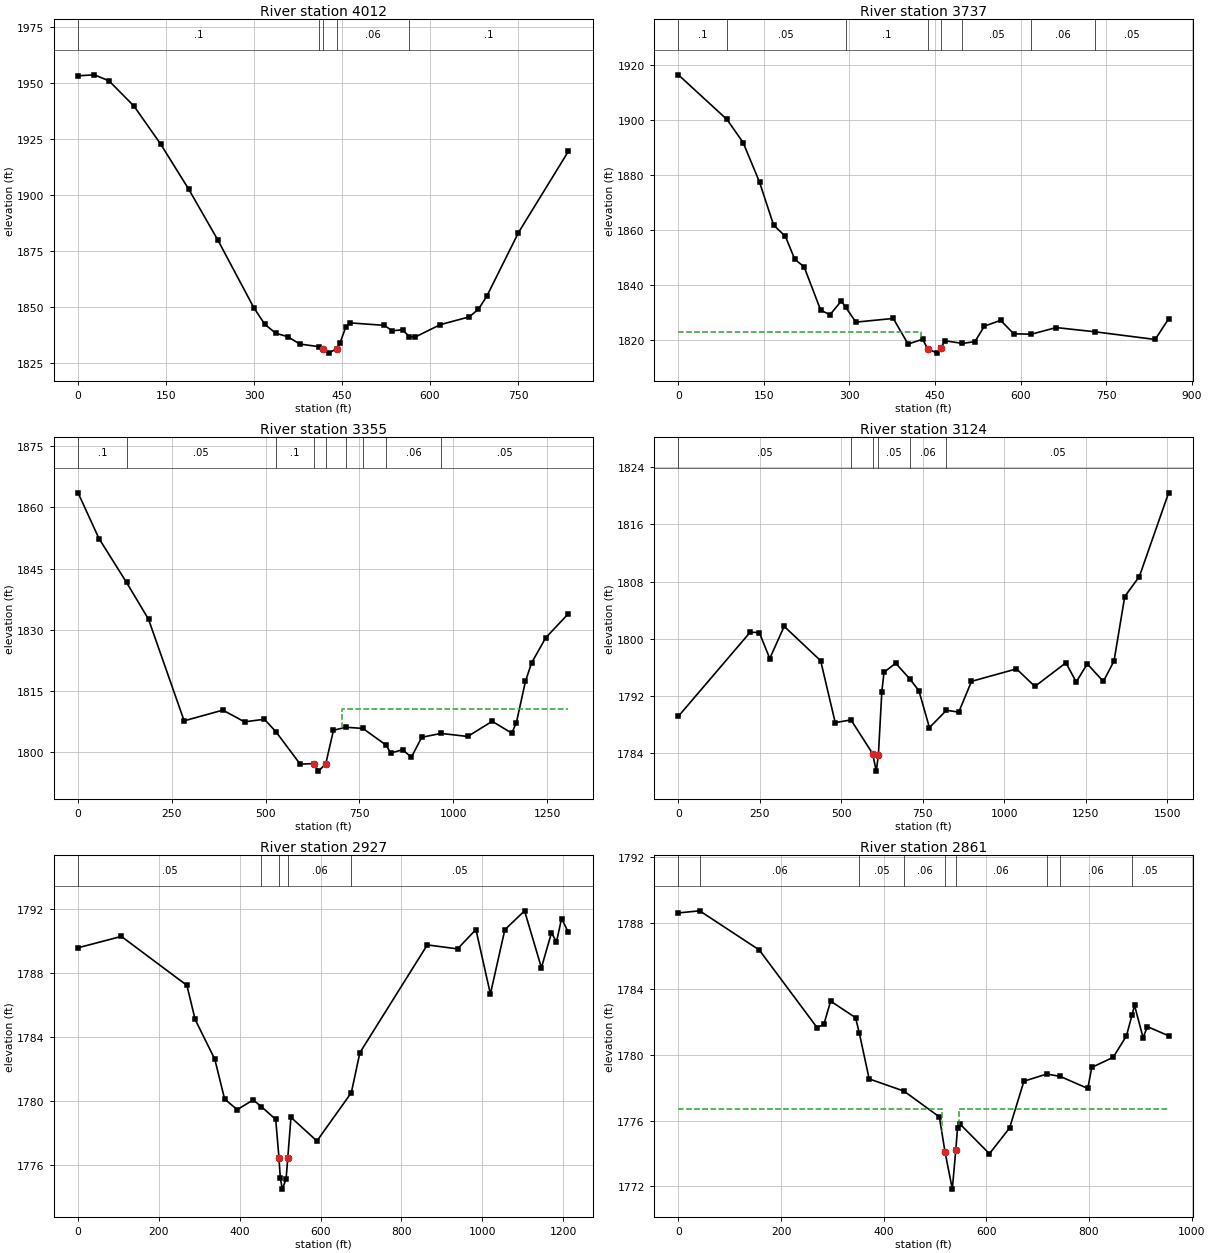
Type RM Length L Ch R = 1 ,4012    ,270.9,274.8,278.1
XS GIS Cut Line= 2
2414986.96274808644080.9433958772414349.98674808643540.027395877
#Sta/Elev= 30
       0 1953.16    27.9 1953.59    52.8 1950.89    95.3 1939.63   140.7  1922.7
   188.6 1902.51     238 1879.94   299.8 1849.47   318.3 1842.17   336.9 1838.17
   357.1 1836.65   378.1 1833.33   411.5 1832.12   416.91831.291   427.3 1829.27
   441.1 1831.31   446.3 1833.67   456.8 1841.16   464.2 1842.77   522.3 1841.67
   535.5 1839.25   553.2 1839.71  564.581836.656   574.8 1836.48   617.4 1841.98
   666.7 1845.46   682.5 1848.84   696.9 1854.76   750.8 1883.13   835.7 1919.36
#Mann= 5 ,-1 , 0
       0      .1       0   411.5     .06       0   416.9    .045       0
   441.1     .06       0  564.58      .1       0
Bank Sta=416.9,441.1
XS Rating Curve= 0 ,0
Exp/Cntr=0.3,0.1

Type RM Length L Ch R = 1 ,3737    ,379.2,382,382.3
XS GIS Cut Line= 3
2415045.63277258644041.1458406712414982.14210746643780.959787872
2414616.15946642643315.955400186
#Sta/Elev= 30
       0 1916.48   85.171900.237   113.5 1891.85   142.3 1877.43     167 1861.78
   187.6 1857.71   204.1 1849.36   220.5 1846.59   249.4 1830.89   265.7 1829.15
   285.7 1834.18  293.18 1831.95   311.2 1826.49   376.8 1827.83   402.7 1818.51
   428.3 1820.26   436.9 1816.83   453.7 1815.21   460.21816.963   467.3 1819.72
  498.081818.741   519.9 1819.39   536.6 1825.03   565.1 1827.14   587.9 1822.26
  618.59 1822.08   662.4 1824.51  730.511822.971     836 1820.18   859.6 1827.69
#Mann= 8 ,-1 , 0
       0      .1       0   85.17     .05       0  293.18      .1       0
   436.9    .045       0   460.2      .1       0  498.08     .05       0
  618.59     .06       0  730.51     .05       0
#XS Ineff= 2 , 0
       0   425.5    1823               0
Permanent Ineff=
       F       F
Bank Sta=436.9,460.2
XS Rating Curve= 0 ,0
Exp/Cntr=0.3,0.1

Type RM Length L Ch R = 1 ,3355    ,231.1,231.1,231.6
XS GIS Cut Line= 4
2415155.19602819644004.9493128092415267.24608342643562.836716432
2415010.61200459643190.8591488392414618.54626974643118.974172257
#Sta/Elev= 30
       0 1863.57    55.8 1852.36  129.171841.611   187.8 1832.59   282.7 1807.69
   385.9 1810.31   443.7 1807.44   496.7 1808.07  527.651804.981   592.1 1797.06
     629 1797.22   640.5 1795.36   660.1  1797.1   680.7 1805.36  713.111806.116
  759.251805.823  821.421801.701   833.1 1799.79   864.8 1800.59   888.5 1798.79
     916 1803.65   967.41804.609  1038.5 1803.85  1103.8 1807.57  1155.9 1804.67
  1168.1 1807.19  1192.5 1817.39  1208.8  1821.9  1246.5 1828.05  1306.6 1833.92
#Mann= 9 ,-1 , 0
       0      .1       0  129.17     .05       0  527.65      .1       0
     629    .045       0   660.1      .1       0  713.11     .05       0
  759.25      .1       0  821.42     .06       0   967.4     .05       0
#XS Ineff= 2 , 0
                          702.87         1810.52
Permanent Ineff=
       F       F
Bank Sta=629,660.1
XS Rating Curve= 0 ,0
Exp/Cntr=0.3,0.1

Type RM Length L Ch R = 1 ,3124    ,196.4,196.7,198.3
XS GIS Cut Line= 4
2415407.30192499643882.7343987642415437.17010761643404.474087202
2415147.72515177643049.2249139922414595.52337475642922.477777364
#Sta/Elev= 30
       0  1789.1   220.3 1800.89   248.3 1800.84   280.4  1797.2   324.5 1801.72
   436.5 1796.89   481.2 1788.21  529.511788.596   595.8 1783.87   607.1 1781.41
   613.6 1783.69   624.2 1792.57   630.9 1795.28   666.8 1796.54   709.31794.375
   737.9 1792.69   770.2 1787.51  822.321789.938   860.2 1789.69   899.2    1794
  1037.3 1795.75  1093.7 1793.29  1188.8  1796.6  1220.6 1793.92  1254.4 1796.45
  1303.7 1793.99  1336.5 1796.85  1369.4  1805.9  1414.2  1808.7    1504 1820.44
#Mann= 6 ,-1 , 0
       0     .05       0  529.51      .1       0   595.8    .045       0
   613.6     .05       0   709.3     .06       0  822.32     .05       0
Bank Sta=595.8,613.6
XS Rating Curve= 0 ,0
Exp/Cntr=0.3,0.1

Type RM Length L Ch R = 1 ,2927    ,60,65.4,66.3
XS GIS Cut Line= 4
     2415616.823      643624.6042415556.12698841643257.821986095
2415348.78367974642987.4985676312414866.63800518642853.791932836
#Sta/Elev= 30
       0 1789.58   107.2 1790.29   269.3 1787.23   289.6  1785.1   338.3 1782.61
   362.6 1780.12   393.8 1779.46   433.2 1780.07  453.77 1779.64     489 1778.85
     4971776.461   500.4 1775.16   505.5 1774.49   514.6 1775.13   518.91776.453
   526.7 1778.98   590.9  1777.5  676.06 1780.52   697.2 1783.02     864 1789.76
   938.8 1789.51   984.3 1790.72  1020.1 1786.69  1055.8 1790.71  1104.6 1791.89
  1146.3 1788.33  1171.2 1790.52  1183.6 1789.94  1196.1 1791.41  1212.8 1790.55
#Mann= 5 ,-1 , 0
       0     .05       0  453.77     .06       0     497    .045       0
   518.9     .06       0  676.06     .05       0
Bank Sta=497,518.9
XS Rating Curve= 0 ,0
Exp/Cntr=0.5,0.3

Type RM Length L Ch R = 1 ,2861    ,59.5,60.6,61.6
XS GIS Cut Line= 4
2415643.68146376643608.0673043542415627.09334042643343.480682412
2415402.18166215642860.7748256682415251.05044184642816.657982114
#Sta/Elev= 30
       0 1788.62   41.521788.747   157.5 1786.37   270.2 1781.65   283.4 1781.84
   296.6 1783.26   345.2 1782.25  352.421781.324   371.7 1778.53  439.481777.788
   508.5 1776.22   519.51774.081   533.7 1771.83   540.41774.197   543.8 1775.52
   548.2  1775.8     606 1773.98   645.3 1775.55   673.2 1778.39  717.791778.828
   744.11778.679   797.6 1777.95   805.4 1779.23     847 1779.84   872.9 1781.14
  883.611782.392   888.7    1783   905.4 1781.03   913.7 1781.71   955.1 1781.15
#Mann= 9 ,-1 , 0
       0     .05       0   41.52     .06       0  352.42     .05       0
  439.48     .06       0   519.5    .045       0   540.4     .06       0
  717.79     .05       0   744.1     .06       0  883.61     .05       0
#XS Ineff= 2 , 0
          513.35 1776.73  547.23         1776.69
Permanent Ineff=
       F       F
Bank Sta=519.5,540.4
XS Rating Curve= 0 ,0
Exp/Cntr=0.5,0.3

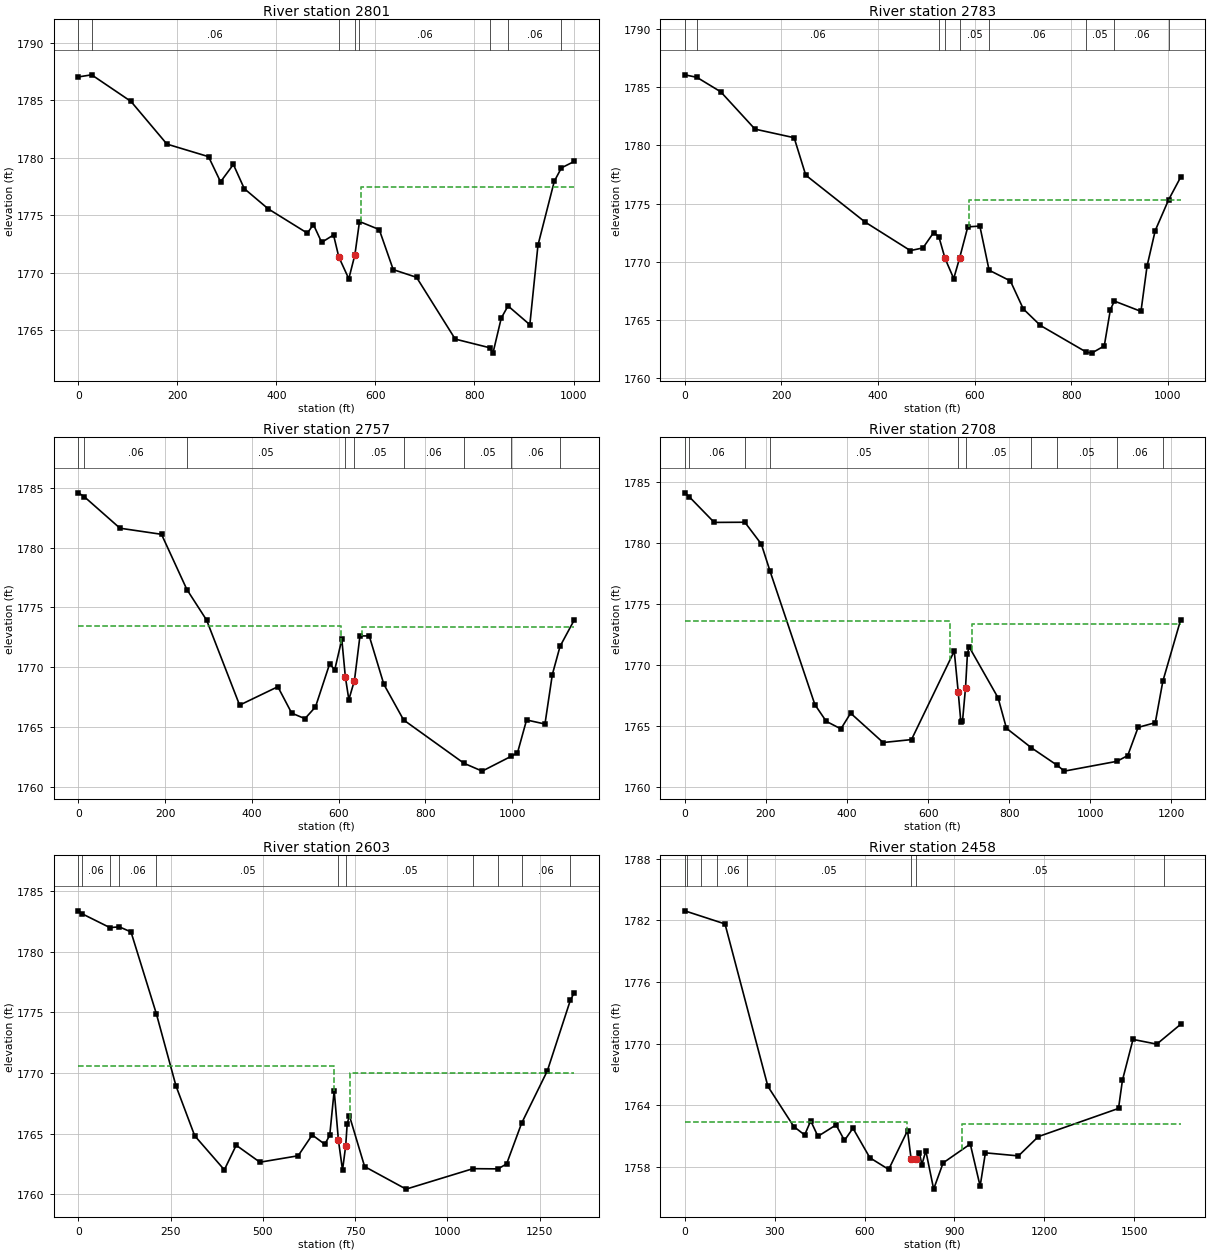
Type RM Length L Ch R = 1 ,2801    ,19.4,17.8,18.2
XS GIS Cut Line= 4
2415665.03607085643589.7108937262415671.08606964643301.439292749
2415443.07739562 642802.065422292415283.78317882642763.133179803
#Sta/Elev= 30
       0 1787.03    26.91787.212   106.3  1784.9   178.9 1781.19   262.9  1780.1
   287.2 1777.91   313.1 1779.42   335.1 1777.32   383.5 1775.56   462.5 1773.45
   474.7  1774.2   491.4 1772.65   515.4 1773.29     526 1771.38   546.2 1769.48
   558.51771.567  567.791774.461   607.7 1773.76   635.9 1770.28     683 1769.61
   761.1 1764.24  831.46 1763.48   837.3 1763.02   854.1 1766.07  867.771767.123
   911.8 1765.49   928.2  1772.4   961.2 1777.96  975.621779.126  1001.3 1779.68
#Mann= 8 ,-1 , 0
       0     .05       0    26.9     .06       0     526    .045       0
   558.5     .05       0  567.79     .06       0  831.46     .05       0
  867.77     .06       0  975.62     .05       0
#XS Ineff= 2 , 0
                          570.43         1777.45
Permanent Ineff=
       F       F
Bank Sta=526,558.5
XS Rating Curve= 0 ,0
Exp/Cntr=0.5,0.3

Type RM Length L Ch R = 1 ,2783    ,44.8,26.3,11.6
XS GIS Cut Line= 4
2415681.10694279643585.2823605742415686.78279884643287.299918224
  2415454.072701642793.5004423322415280.95909164642735.322917873
#Sta/Elev= 30
       0 1786.07   24.961785.857    74.4 1784.61   145.3  1781.4   226.4 1780.66
   250.4 1777.44   373.5  1773.4     467 1770.95   493.1 1771.18   515.2  1772.5
  525.991772.151   538.8 1770.28   556.8 1768.54   568.9  1770.3   585.9 1772.99
   610.9 1773.06  630.061769.264   674.1 1768.34   700.9 1765.93   736.3 1764.51
     8311762.225   842.4 1762.13   868.5 1762.75   881.2 1765.88  889.461766.608
   944.5 1765.72   957.1 1769.62     974 1772.67 1001.721775.321  1026.6 1777.26
#Mann= 9 ,-1 , 0
       0     .05       0   24.96     .06       0  525.99     .05       0
   538.8    .045       0   568.9     .05       0  630.06     .06       0
     831     .05       0  889.46     .06       0 1001.72     .05       0
#XS Ineff= 2 , 0
                          588.91         1775.33
Permanent Ineff=
       F       F
Bank Sta=538.8,568.9
XS Rating Curve= 0 ,0
Exp/Cntr(USF)=0,0
Exp/Cntr=0.5,0.3

Type RM Length L Ch R = 1 ,2757    ,49,49.3,48.7
XS GIS Cut Line= 5
2415704.04671209643570.5819280222415695.44750164 643049.05642693
2415577.93671281643030.9922224492415466.04052727642761.707986075
2415267.22040553642691.836594176
#Sta/Elev= 30
       0 1784.59   13.711784.264      96 1781.63   191.7 1781.12  250.221776.501
   295.7 1773.94   371.7 1766.83   459.8 1768.37   491.8 1766.16   522.3  1765.7
   546.6 1766.68     579 1770.26   591.1 1769.81   607.3 1772.33   615.4  1769.2
   623.5 1767.29   636.4 1768.89   649.1 1772.62   670.5 1772.62   704.2 1768.57
   749.71765.591  888.891761.965   930.8 1761.31  997.211762.543  1012.2 1762.84
  1033.1 1765.59  1075.5 1765.25  1092.5 1769.39  1110.3 1771.75  1142.8 1773.94
#Mann= 9 ,-1 , 0
       0     .05       0   13.71     .06       0  250.22     .05       0
   615.4    .045       0   636.4     .05       0   749.7     .06       0
  888.89     .05       0  997.21     .06       0  1110.3     .05       0
#XS Ineff= 2 , 0
          604.93 1773.48  652.98         1773.34
Permanent Ineff=
       F       F
Bank Sta=615.4,636.4
XS Rating Curve= 0 ,0
Exp/Cntr=0.5,0.3

Type RM Length L Ch R = 1 ,2708    ,93.8,104.3,112.8
XS GIS Cut Line= 5
2415709.29708947643567.3602322252415734.56777559643008.900190997
2415573.67250928642981.1861992042415475.97683711642737.521699203
2415251.85147154642658.215800617
#Sta/Elev= 30
       0 1784.14   11.43  1783.8    72.5 1781.71  148.021781.724   188.7 1779.93
  210.44 1777.68   320.8 1766.74   348.8 1765.37   384.9 1764.75   408.9 1766.04
     489 1763.63     559 1763.87   664.4 1771.14   674.11767.808   680.6 1765.35
   684.7 1765.36   692.2 1768.13   696.9 1770.91   700.9  1771.5   772.5  1767.3
   793.1  1764.8  854.781763.194  918.771761.747   935.9 1761.28 1065.611762.086
  1092.2 1762.56  1117.7 1764.87  1160.1 1765.26 1178.831768.673  1222.6  1773.7
#Mann= 10 ,-1 , 0
       0     .05       0   11.43     .06       0  148.02     .06       0
  210.44     .05       0   674.1    .045       0   692.2     .05       0
  854.78     .06       0  918.77     .05       0 1065.61     .06       0
 1178.83     .05       0
#XS Ineff= 2 , 0
             654 1773.62  707.19         1773.38
Permanent Ineff=
       F       F
Bank Sta=674.1,692.2
XS Rating Curve= 0 ,0
Exp/Cntr(USF)=0,0
Exp/Cntr=0.5,0.3

Type RM Length L Ch R = 1 ,2603    ,140.4,145,149.5
XS GIS Cut Line= 4
2415718.41479281643565.0499142192415765.88392362643014.800091573
2415510.32928563642736.622583996 2415159.3593074642518.245172034
#Sta/Elev= 30
       0 1783.37   10.62 1783.12   85.561781.986  111.041782.048   142.7 1781.63
  211.461774.874   264.7 1768.92   315.3 1764.82   395.6 1762.01   427.7 1764.04
     492 1762.64   595.6 1763.17   633.7 1764.89   667.7 1764.12   681.1 1764.85
   693.2 1768.54   704.7 1764.45   715.8 1761.99   724.41763.991   728.4 1765.79
   734.3 1766.49   775.7 1762.28     888 1760.42 1069.271762.107 1137.13 1762.09
  1160.4  1762.5 1201.071765.858  1270.8 1770.18 1332.861775.977  1343.4 1776.61
#Mann= 11 ,-1 , 0
       0     .05       0   10.62     .06       0   85.56    .055       0
  111.04     .06       0  211.46     .05       0   704.7    .045       0
   724.4     .05       0 1069.27     .06       0 1137.13    .055       0
 1201.07     .06       0 1332.86     .05       0
#XS Ineff= 2 , 0
          692.81 1770.55  737.37         1769.99
Permanent Ineff=
       F       F
Bank Sta=704.7,724.4
XS Rating Curve= 0 ,0
Exp/Cntr(USF)=0,0
Exp/Cntr=0.3,0.1

Type RM Length L Ch R = 1 ,2458    ,103.7,114.1,128.2
XS GIS Cut Line= 4
2415723.71388599643560.1073707682415804.35317087642884.513809634
2415694.58724443642632.8265568272415058.25628088642341.872885355
#Sta/Elev= 30
       0 1782.94   134.2 1781.66   277.3 1765.82   363.8  1761.9     400 1761.08
   420.2 1762.46   444.3 1760.95   504.8 1762.06   532.9 1760.55   561.2 1761.74
   617.6 1758.86   680.4 1757.72   743.3  1761.5   755.11758.774   771.41758.742
   783.1 1759.32   791.3 1758.19   804.3 1759.54   830.5  1755.8   862.1 1758.36
   952.7  1760.2   985.6 1756.09  1003.2 1759.34  1113.5 1759.04  1179.7 1760.92
  1447.4 1763.67  1460.6 1766.43  1495.8  1770.4  1575.1 1769.94  1654.7 1771.87
#Mann= 8 ,-1 , 0
       0     .05       0    6.49     .06       0   53.93    .055       0
  107.77     .06       0  209.06     .05       0   755.1    .045       0
   771.4     .05       0 1600.35     .06       0
#XS Ineff= 2 , 0
          740.12 1762.35   923.6         1762.11
Permanent Ineff=
       F       F
Bank Sta=755.1,771.4
XS Rating Curve= 0 ,0
Exp/Cntr(USF)=0,0
Exp/Cntr=0.3,0.1

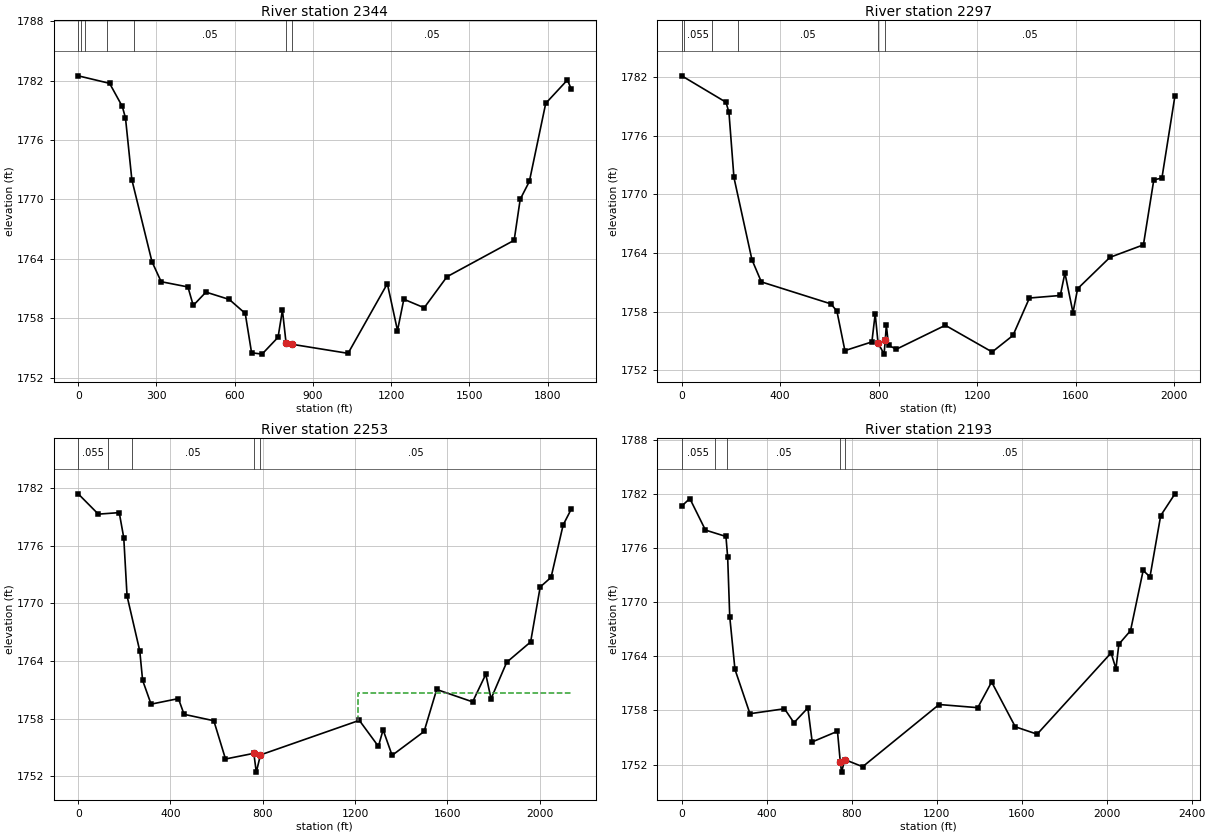
Type RM Length L Ch R = 1 ,2344    ,32.3,47.2,57.9
XS GIS Cut Line= 4
2415730.46116302643561.6136847292415858.05874922642814.478169968
2415898.61410517642710.6758424282415058.16521547642130.619177959
#Sta/Elev= 30
       0 1782.48   120.4 1781.72     169 1779.39   181.3 1778.22   205.7 1771.99
   282.8 1763.72     318  1761.7   420.7 1761.17     441  1759.3   489.7 1760.65
     579 1759.91   640.3  1758.5   664.6 1754.53   704.8 1754.39   766.1 1756.09
   782.9 1758.83     7971755.477   819.31755.385  1034.5 1754.47  1185.1  1761.5
    1224 1756.77  1248.3 1759.93  1326.4 1759.07  1413.6  1762.2  1671.2 1765.88
  1694.4 1770.02  1729.5 1771.82  1792.2  1779.7  1875.3 1782.06  1890.6 1781.12
#Mann= 7 ,-1 , 0
       0     .05       0    9.25     .06       0   26.12    .055       0
  112.12     .06       0  214.98     .05       0     797    .045       0
   819.3     .05       0
#XS Ineff= 2 ,-1
   -5.11  792.08    1755   822.7  1278.4    1755
Permanent Ineff=
       F       F
Bank Sta=797,819.3
XS Rating Curve= 0 ,0
Exp/Cntr(USF)=0,0
Exp/Cntr=0.5,0.3

Type RM Length L Ch R = 1 ,2297    ,43.1,43.5,42.4
XS GIS Cut Line= 5
2415737.28494785643571.7463353912415869.72158889642816.542156101
2416018.61409813642738.7609471632415827.12474766642529.399257319
2415157.54843609642119.017457981
#Sta/Elev= 30
       0 1782.12   179.6 1779.42   191.7 1778.38     212 1771.72   285.1 1763.31
   323.3 1761.04     606 1758.79   630.3 1758.05   662.8 1754.01   772.4  1754.9
   785.9 1757.77   797.41754.802     822 1753.65   826.91755.082   831.1 1756.61
   840.1 1754.56   871.7 1754.15  1070.8  1756.6  1261.1 1753.87  1345.6 1755.56
  1412.5 1759.39  1537.9 1759.65  1556.7 1761.95  1589.5  1757.9  1608.3 1760.34
  1739.6 1763.55  1875.7 1764.83  1917.9 1771.48  1950.8 1771.66  2003.8 1780.07
#Mann= 6 ,-1 , 0
       0     .05       0    10.2    .055       0  123.97     .06       0
  226.98     .05       0   797.4    .045       0   826.9     .05       0
Bank Sta=797.4,826.9
XS Rating Curve= 0 ,0
Exp/Cntr(USF)=0,0
Exp/Cntr=0.5,0.3

Type RM Length L Ch R = 1 ,2253    ,60.3,60.3,60.3
XS GIS Cut Line= 5
     2415746.192      643572.3792415893.83882631642852.812613246
 2416074.7843076  642754.08009522415799.03964293642404.292881681
2415135.11504184642051.494252595
#Sta/Elev= 30
       0 1781.44    87.3 1779.32   177.9 1779.48   197.5 1776.86   211.8 1770.78
   266.9 1765.05   279.2 1761.99   315.9  1759.5   434.4 1760.08   458.9 1758.44
   587.9 1757.77   638.5 1753.78   761.3 1754.37     772 1752.41   790.11754.206
  1218.6 1757.81  1301.3  1755.1  1321.7 1756.82  1360.7 1754.16  1499.4 1756.65
    1554 1761.03  1709.8 1759.74  1766.9 1762.62  1789.6 1760.06  1857.5 1763.87
  1961.2 1765.99  2002.6 1771.72  2049.9 1772.73  2102.1 1778.19  2137.9 1779.87
#Mann= 5 ,-1 , 0
       0    .055       0  127.37     .06       0  231.45     .05       0
   761.3    .045       0   790.1     .05       0
#XS Ineff= 2 , 0
                         1211.15         1760.71
Permanent Ineff=
       F       F
Bank Sta=761.3,790.1
XS Rating Curve= 0 ,0
Exp/Cntr=0.5,0.3

Type RM Length L Ch R = 1 ,2193    ,,,
XS GIS Cut Line= 5
     2415768.803       643596.042415910.83699764642906.542740565
2416128.40132573 642810.250304672415962.44388866642419.612029718
 2415128.0166795641955.555173605
#Sta/Elev= 30
       0 1780.67    37.9 1781.51   111.4 1778.01   207.9  1777.3     216 1775.02
   225.8  1768.4   250.3 1762.56   320.9 1757.64   483.5 1758.19     528 1756.64
   593.4 1758.28   613.8 1754.51   732.8 1755.69     7461752.307     752 1751.16
   767.21752.552   851.4 1751.76  1211.1 1758.66  1393.1 1758.31  1458.3 1761.16
  1569.6 1756.19  1672.5 1755.37  2020.5 1764.38  2043.4 1762.63  2057.1 1765.35
    2112 1766.85  2171.5 1773.53  2203.6 1772.82  2253.9 1779.61  2321.1 1782.03
#Mann= 5 ,-1 , 0
       0    .055       0  156.07     .06       0  211.96     .05       0
     746    .045       0   767.2     .05       0
Bank Sta=746,767.2
XS Rating Curve= 0 ,0
Exp/Cntr=0.3,0.1
LCMann Table=0

Chan Stop Cuts=-1
Use User Specified Reach Order=0
Composite Channel Slope=5